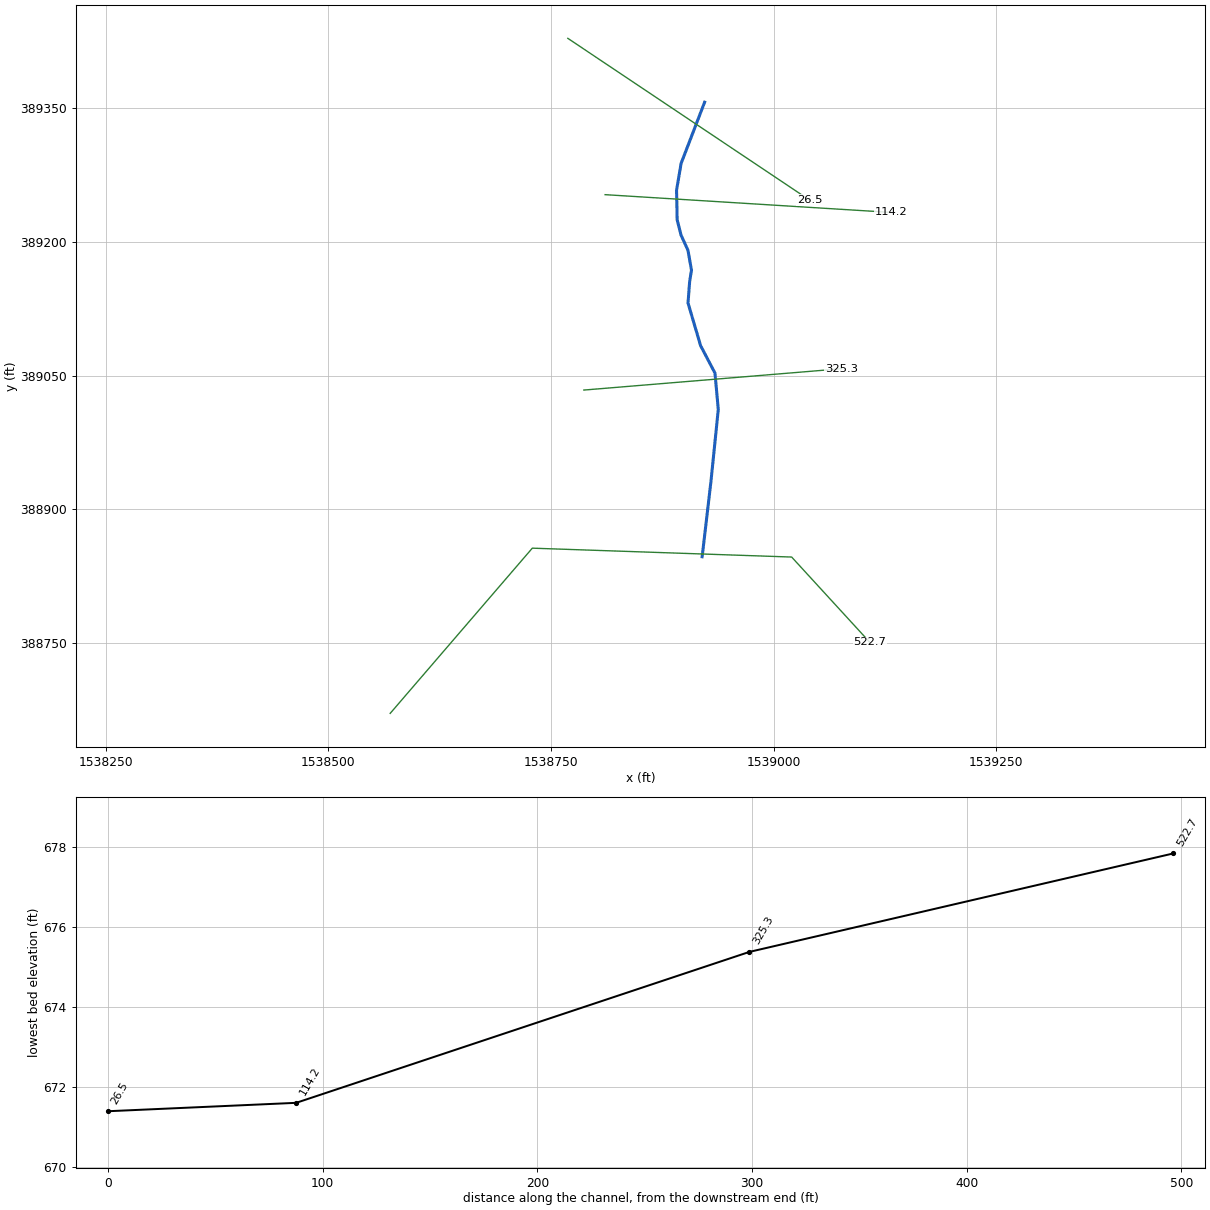
--- FLATBRWST.prj (project) ---

Proj Title=FLATBRWST
Current Plan=p01
Default Exp/Contr=0,0
English Units
Geom File=g01
Flow File=f01
Plan File=p01
BEGIN DESCRIPTION:
END DESCRIPTION:
DSS Export Rating Curves= 0
DSS Export Rating Curve Sorted= 0
DSS Export Volume Flow Curves= 0
DXF OffsetX= 0
DXF OffsetY= 0
DXF ScaleX= 0
DXF ScaleY= 0

--- FLATBRWST.p01 (plan) ---

Plan Title=Floodplain
Program Version=4.00
Geom File=g01
Flow File=f01
K Sum by GR=0
Std Step Tol=0.01
Critical Tol=0.01
Num of Std Step Trials=20
Max Error Tol=0.3
Flow Tol Ratio=0.001
Split Flow NTrial=30
Split Flow Tol=0.02
Split Flow Ratio=0.02
Log Output Level=0
Friction Slope Method=1
Unsteady Friction Slope Method=2
Unsteady Bridges Friction Slope Method=1
Global Log Level=0
CheckData=False
Run HTab=0
Run UNet=0
Run PostProcess=0
UNET Theta=0
UNET Theta Warmup=0
UNET ZTol=0
UNET ZSATol=0
UNET MxIter=0
UNET MaxInSteps=0
UNET DtIC=0
UNET DtMin=0
UNET MaxCRTS=0
UNET WFStab=0
UNET SFStab=0
UNET WFX=0
UNET SFX=0
UNET DSS MLevel=0
UNET DZMax Abort=0
UNET Convert EG Bridges=0
UNET Use Existing IB Tables=0
UNET Froude Limit=0
UNET Froude Power=0
Write IC File=0
Echo Input=False
Echo Output=False
Write Detailed=0

--- FLATBRWST.f01 (steady flow) ---

Flow Title=NFF Regression Equation
Program Version=4.00
Number of Profiles=1
Profile Names=P100yr
River Rch & RM=FLATBRWST,Main      ,522.7
357.6627
Boundary for River Rch & Prof#=FLATBRWST,Main      ,1
Up Type=0
Dn Type=3
Dn Slope=0.010891

--- FLATBRWST.g01 (geometry) ---

Geom Title=Geometry
Program Version=4.00

River Reach=FLATBRWST       ,Main
Reach XY= 15
     1538919.795      388846.535      1538920.39      388851.633
     1538929.717      388931.468     1538937.918      389012.046
     1538934.182      389052.828     1538918.071      389083.552
     1538903.927      389131.522     1538905.764      389155.669
     1538907.804      389168.395     1538903.867      389190.742
      1538896.08      389207.779     1538891.723      389224.944
     1538891.053      389258.288      1538896.17      389288.305
     1538922.571      389357.051

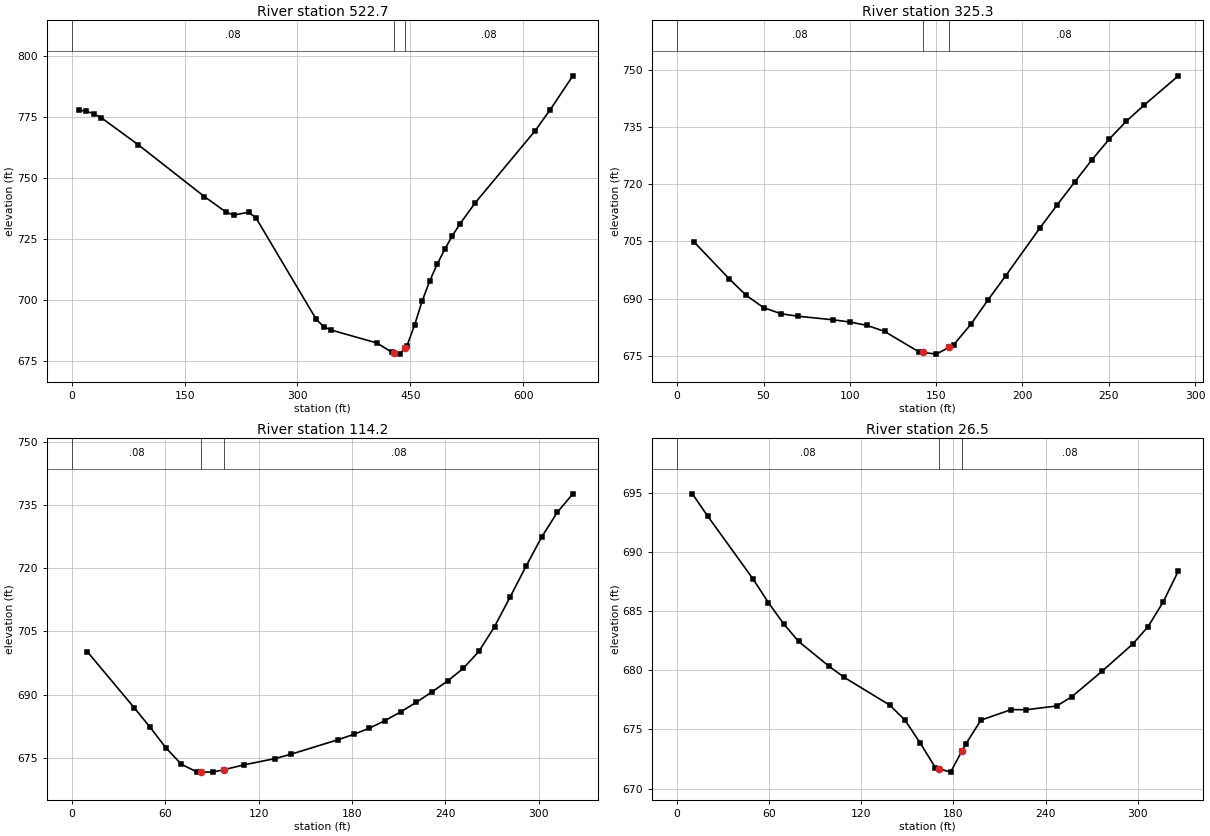
Type RM Length L Ch R = 1 ,522.7   ,194.8,197.5,200.1
XS GIS Cut Line= 4
     1538569.436      388670.634     1538729.042      388856.176
     1539020.323      388846.201     1539108.106      388750.437
#Sta/Elev= 30
     9.8  777.78    19.6  777.33    29.4  776.33    39.2  774.71    88.1   763.7
   176.2  742.42   205.6  735.92   215.4  734.81     235  735.95   244.7  733.76
   325.1  692.03   335.2  688.99   345.2  687.67   405.5   682.4   425.6  678.61
   428.2  678.41   435.7  677.83   443.2  680.47   445.7  681.36   455.8  689.83
   465.8  699.62   475.9  707.88   485.9  714.81     496   720.9     506  726.38
   516.1  731.23   536.2  739.79   616.1  769.43   636.1  778.06   666.1  791.87
#Mann= 3 , 0 , 0
       0     .08       0   428.2    .045       0   443.2     .08       0
Bank Sta=428.2,443.2
XS Rating Curve= 0 ,0
Exp/Cntr=0.3,0.1

Type RM Length L Ch R = 1 ,325.3   ,214.3,211.1,207.9
XS GIS Cut Line= 2
     1538786.899      389033.738     1539076.185      389057.679
#Sta/Elev= 26
      10  704.77      30  695.24      40  690.82      50  687.61    60.1     686
    70.1  685.33    90.1  684.41   100.1  683.81   110.1  682.91   120.1  681.35
   140.1  675.94   142.6   675.8   150.1  675.37   157.6   677.2   160.2  677.84
   170.2  683.27   180.2  689.72   190.2  695.92   210.2  708.61   220.2  714.67
   230.2  720.62   240.2  726.46   250.2   731.9   260.2  736.65   270.3   740.8
   290.3  748.58
#Mann= 3 , 0 , 0
       0     .08       0   142.6    .045       0   157.6     .08       0
Bank Sta=142.6,157.6
XS Rating Curve= 0 ,0
Exp/Cntr=0.3,0.1

Type RM Length L Ch R = 1 ,114.2   ,99.7,87.7,75.7
XS GIS Cut Line= 2
      1538810.84      389253.196     1539132.047      389233.245
#Sta/Elev= 28
    10.1  700.13    40.2  686.84    50.3  682.27    60.3  677.44    70.4  673.46
    80.5  671.62      83  671.62    90.5   671.6      98   672.2   110.6  673.33
   130.7  674.82   140.8  675.85     171  679.29     181  680.54   191.1  682.03
   201.1  683.82   211.2  685.88   221.3  688.17   231.3  690.63   241.4  693.24
   251.4  696.21   261.5  700.27   271.5  706.13   281.6  713.21   291.7  720.44
   301.7  727.34   311.8  733.25   321.8  737.63
#Mann= 3 , 0 , 0
       0     .08       0      83    .045       0      98     .08       0
Bank Sta=83,98
XS Rating Curve= 0 ,0
Exp/Cntr=0.3,0.1

Type RM Length L Ch R = 1 ,26.5    ,21.4,26.5,31.6
XS GIS Cut Line= 2
     1538768.943      389428.763     1539040.274      389247.211
#Sta/Elev= 26
     9.9  694.94    19.8  693.07    49.5  687.72    59.4  685.74    69.3  683.95
    79.1  682.45    98.9  680.35   108.8  679.41   138.5  677.06   148.4  675.79
   158.3  673.86   168.2  671.77   170.6  671.68   178.1  671.39   185.6  673.19
     188  673.76   197.9  675.79   217.6  676.68   227.5  676.67   247.3  676.99
   257.2  677.78     277  679.95   296.8  682.23   306.7  683.69   316.6  685.78
   326.5  688.41
#Mann= 3 , 0 , 0
       0     .08       0   170.6    .045       0   185.6     .08       0
Bank Sta=170.6,185.6
XS Rating Curve= 0 ,0
Exp/Cntr=0.3,0.1

Chan Stop Cuts=-1
Use User Specified Reach Order=0